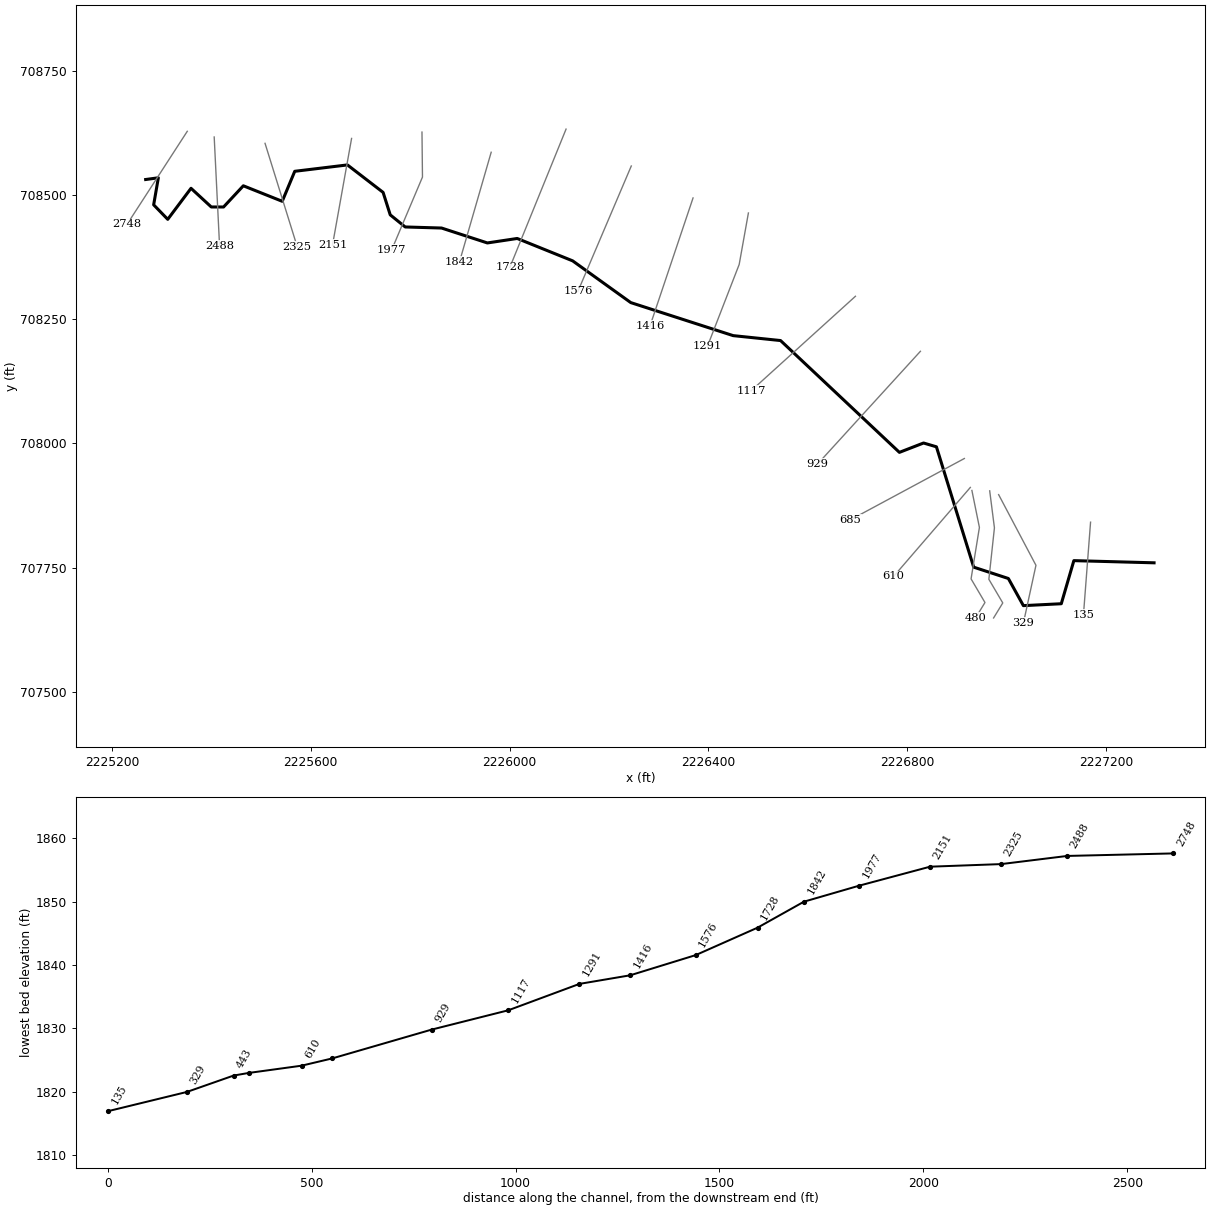
--- WOAKRN.prj (project) ---

Proj Title=WOAKRN
Current Plan=p01
Default Exp/Contr=0,0
English Units
Geom File=g01
Flow File=f01
Plan File=p01
BEGIN DESCRIPTION:
---------- MODELED AS PART OF WVEMD CTP PROGRAM, 2023----------
Stream Name: White Oak Run
Flood Zone:  AFH
Upshur County, WV
HEC-RAS Version: RAS 6.3
Vertical Datum: NAVD88
Projection: NAD 1983 StatePlane West Virginia S FIPS 4702 (US Feet)
Terrain: 1-meter LIDAR (FEMA Region III 3DEP collected 2016-2018)
Land Use: 2019 NLCD
Hydrologic Method:
WV 2010 Regional Regression Equations
Additional Model Notes:
None
END DESCRIPTION:
DSS Export Rating Curves= 0
DSS Export Rating Curve Sorted= 0
DSS Export Volume Flow Curves= 0
DXF OffsetX= 0
DXF OffsetY= 0
DXF ScaleX= 0
DXF ScaleY= 0

--- WOAKRN.p01 (plan) ---

Plan Title=Floodplain
Program Version=6.31
Geom File=g01
Flow File=f01
Subcritical Flow
K Sum by GR= 0
Std Step Tol= 0.01
Critical Tol= 0.01
Num of Std Step Trials= 20
Max Error Tol= 0.3
Flow Tol Ratio= 0.001
Split Flow NTrial= 30
Split Flow Tol= 0.02
Split Flow Ratio= 0.02
Log Output Level= 0
Friction Slope Method= 1
Unsteady Friction Slope Method= 2
Unsteady Bridges Friction Slope Method= 1
Parabolic Critical Depth
Global Vel Dist= 0 , 0 , 0
Global Log Level= 0
CheckData=False
Encroach Param=-1 ,0,0, 0
Mapping Interval=1HOUR
Computation Time Step Use Courant=        0
Computation Time Step Use Time Series=    0
Computation Time Step Count To Double=0
Computation Time Step Max Doubling=0
Computation Time Step Max Halving=0
Computation Time Step Residence Courant=0
Run HTab= 0
Run UNet= 0
Run Sediment= 0
Run PostProcess= 0
Run WQNet= 0
Run RASMapper= 0
UNET Theta= 0
UNET Theta Warmup= 0
UNET ZTol= 0
UNET ZSATol= 0
UNET MxIter= 0
UNET Max Iter WO Improvement= 0
UNET MaxInSteps= 0
UNET DtIC= 0
UNET DtMin= 0
UNET MaxCRTS= 0
UNET WFStab= 0
UNET SFStab= 0
UNET WFX= 1
UNET SFX= 1
UNET Gravity=32.17405
UNET 1D Methodology=Finite Difference
UNET DSS MLevel= 1
UNET Pardiso=0
UNET DZMax Abort= 0
UNET Use Existing IB Tables= 0
UNET Froude Reduction=False
UNET Froude Limit= 0
UNET Froude Power= 0
UNET D1 Cores= 0
UNET WindReference=Eulerian
UNET WindDragFormulation=Hsu (1988)
UNET D2 Coriolis=0
UNET D2 Cores= 0
UNET D2 Theta= 1
UNET D2 Theta Warmup= 1
UNET D2 Z Tol= 0.01
UNET D2 Volume Tol= 0.01
UNET D2 Max Iterations= 20
UNET D2 Equation= 0
UNET D2 RampUpFraction=0.1
UNET D2 TimeSlices= 1
UNET D2 Turbulence Formulation=Non-Conservative (original)
UNET D2 Eddy Viscosity=0.3
UNET D2 Transverse Eddy Viscosity=0.1
UNET D2 Smagorinsky Mixing=0
UNET D2 BCVolumeCheck=0
UNET D2 Cores=0
UNET D2 SolverType=PARDISO (Direct)
UNET D2 Minimum Iterations= 3
UNET D2 Maximum Iterations= 30
UNET D2 Restart Number= 10
UNET D2 Relaxation Coeff=1.3
UNET D2 SOR Precondition Iterations= 10
UNET D2 ILUT Maximum Fill= 8
UNET D2 ILUT Tolerance=1E-08
UNET D2 Convergence Tolerance=0.00001
UNET D1D2 MaxIter= 0
UNET D1D2 ZTol=0.01
UNET D1D2 QTol=0.1
UNET D1D2 MinQTol=1
Write IC File= 0
Write IC File at Fixed DateTime=0
Write IC File at Sim End=0
Echo Input=False
Echo Parameters=False
Echo Output=False
Write Detailed= 0
HDF Write Warmup=0
HDF Write Time Slices=0
HDF Flush=0
HDF Compression= 1
HDF Chunk Size= 1
HDF Spatial Parts= 1
HDF Use Max Rows=0
HDF Fixed Rows= 1
Calibration Method= 0
Calibration Iterations= 20
Calibration Max Change=0.05
Calibration Tolerance=0.2
Calibration Maximum=1.5
Calibration Minimum=0.5
Calibration Optimization Method= 1
WQ AD Non Conservative
WQ ULTIMATE=-1
WQ Max Comp Step=1HOUR
WQ Output Interval=15MIN
WQ Output Selected Increments= 0
WQ Create Restart=0
WQ Fixed Restart=0
WQ System Summary=0
WQ Write To DSS=0
Sorting and Armoring Iterations= 10
XS Update Threshold= 0.02
Bed Roughness Predictor= 0
Hydraulics Update Threshold= 0.02
Energy Slope Method= 1
Volume Change Method= 1
Sediment Retention Method= 0
Sediment TS Multiplier= 1
Warm Up Method= 0
XS Weighting Method= 0
Number of US Weighted Cross Sections= 1
Number of DS Weighted Cross Sections= 1
Upstream XS Weight=0
Main XS Weight=1
Downstream XS Weight=0
Number of DS XS's Weighted with US Boundary= 1
Upstream Boundary Weight= 1
Weight of XSs Associated with US Boundary= 0
Number of US XS's Weighted with DS Boundary= 1
Downstream Boundary Weight= 0.5
Weight of XSs Associated with DS Boundary= 0.5
Percentile Method= 0
Sediment Output Level= 3
Mass or Volume Output= 0
Output Increment Type= 1
Profile and TS Output Increment= 1
Transport Output Increment 1
XS Output Flag= 0
XS Output Increment= 10
Read HDF5 Sediment Hotstart= 0
Sediment Hotstart Type= 0
Write Gradation File= 0
Read Gradation Hotstart= 0
Write HDF5 File= 1
Write Binary Output= 1
Write DSS Sediment File= 0
DSS Sediment Output Type= 1
SV Curve= 0
Specific Gage Flag= 0
Subcell Erosion Methods= 0
Subcell Deposition Methods= 0
Advection Scheme= 1
Matrix Solver= 0
Implicit Weighting Factor= 1
Maximum Outer Loop Convergence Iterations= 5
Convergence Maximum Absolute= 0.001
Convergence RMSE= 0.0001
Grain Fractions Max Abs Error= 0.001
Max Subgrid Regions= 1
Max Subgrid Length Scale= 3.402823E+38
Initial Layer Thickness= 3.402823E+38
Min Layer Thickness= 3.402823E+38
Max Layer Thickness= 3.402823E+38
Number of Layers= 5

--- WOAKRN.f01 (steady flow) ---

Flow Title=Flows
Program Version=6.31
Number of Profiles= 1
Profile Names=01pct
River Rch & RM=WOAKRN,Main            ,2748
     355
Boundary for River Rch & Prof#=WOAKRN,Main            , 1
Up Type= 0
Dn Type= 3
Dn Slope=0.01568
DSS Import GetInterval= 0
DSS Import GetPeak= 0
DSS Import FillOption= 0

--- WOAKRN.g01 (geometry) ---

Geom Title=Geometry
Program Version=6.31

River Reach=WOAKRN          ,Main
Reach XY= 30
2225267.84016208708530.6962840292225293.36693881708534.152002228
2225283.95763957708479.787162157 2225312.2683914708450.585088313
2225359.10291071708513.0225426162225399.86089332708475.456383059
2225424.57012585708475.4089436822225464.34300049708518.080148813
2225542.62777592708486.865344359 2225567.8048334708547.220473399
2225673.77257839 708560.05614262 2225745.5565738 708504.79191661
 2225759.8978316708459.6169545382225790.01447298708435.236816277
2225863.15488777708433.0856276072225955.30694555708403.085337902
2226015.37519815708412.073494242     2226126.899      708367.055
     2226243.854      708283.066     2226449.806      708216.619
     2226545.156      708206.717     2226784.275      707981.764
     2226832.837      708000.594     2226858.735      707992.953
     2226933.709       707750.83     2227003.505      707727.994
     2227033.695      707673.394     2227109.958      707677.228
     2227135.255      707763.936     2227296.622      707759.558

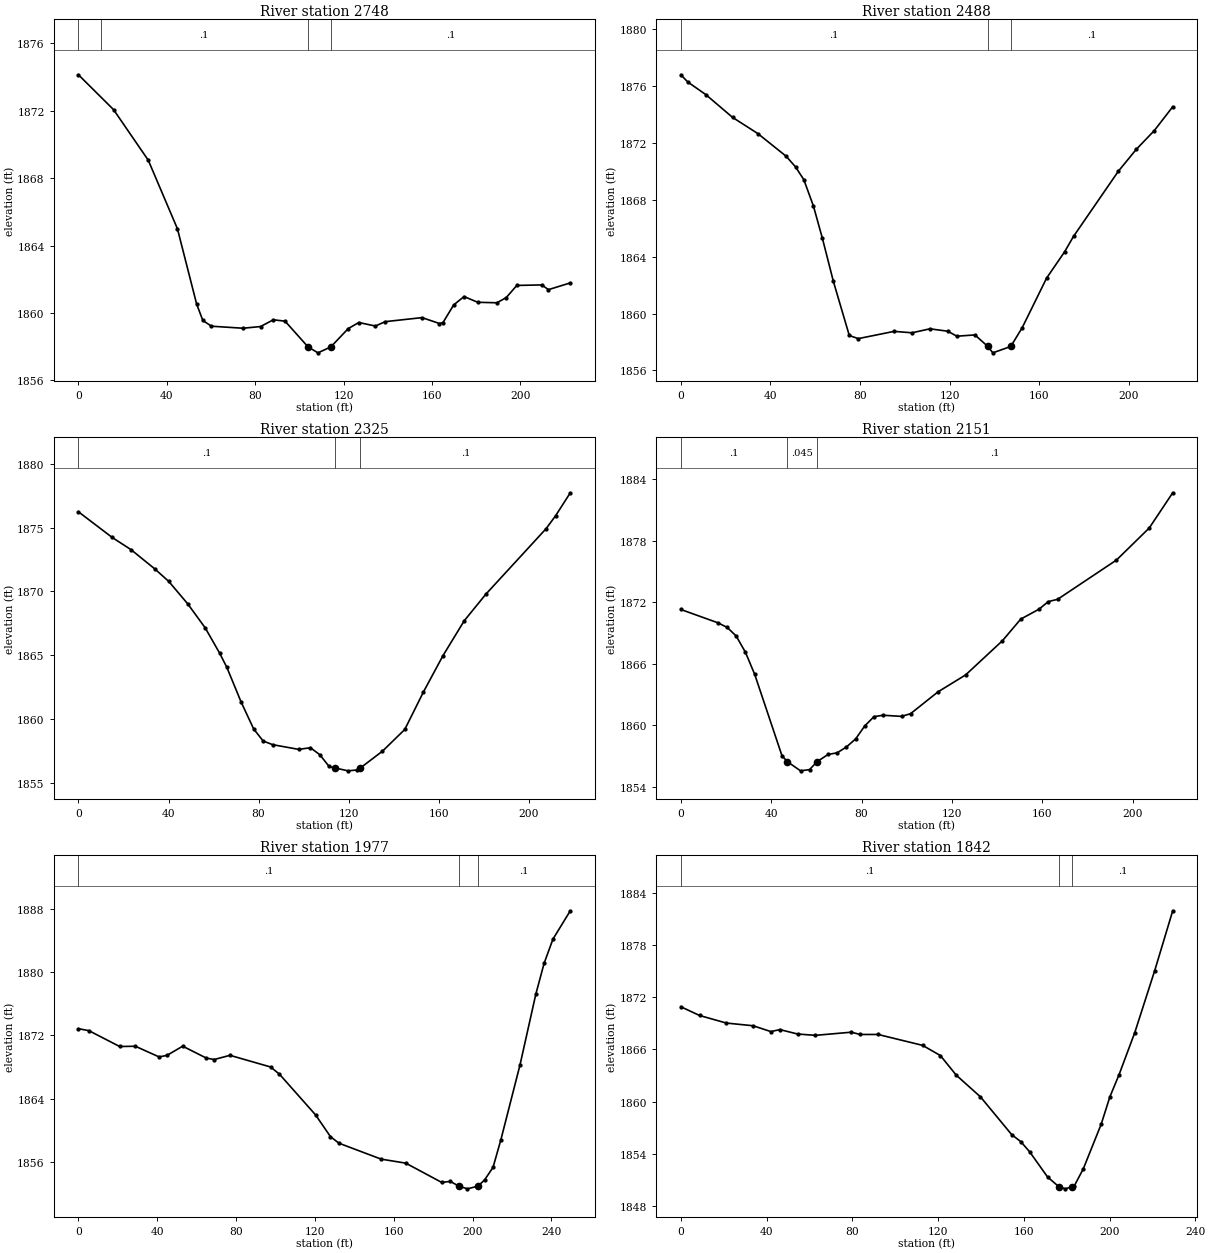
Type RM Length L Ch R = 1 ,2748    ,260.4,260.4,260.4
XS GIS Cut Line= 2
2225351.57935055708627.6986337662225230.59343083 708440.80981469
#Sta/Elev= 30
       0 1874.14    15.9 1872.07    31.6 1869.07    44.8    1865    53.5 1860.53
    56.3 1859.56    60.2 1859.22    74.5  1859.1    82.4  1859.2    88.2  1859.6
    93.5 1859.52  103.911857.992   108.4 1857.64   114.2 1857.99   122.1 1859.08
   126.9 1859.44   134.4 1859.23   138.8 1859.49   155.5 1859.73   163.4 1859.38
     165 1859.44   169.8 1860.48   174.5 1860.98   180.7 1860.64   189.4 1860.61
   193.6 1860.92   198.4 1861.64   209.7 1861.67   212.7 1861.39   222.6 1861.79
#Mann= 4 ,-1,0
       0     .06       0      10      .1       0  103.91    .045       0
   114.2      .1       0
Bank Sta=103.91,114.2
XS Rating Curve= 0 ,0
Exp/Cntr(USF)=0,0
Exp/Cntr=0.3,0.1

Type RM Length L Ch R = 1 ,2488    ,153.2,162.1,162.5
XS GIS Cut Line= 2
2225405.73919331708616.2757613862225416.55907231708396.927305312
#Sta/Elev= 30
       0  1876.8     3.1 1876.29    11.1 1875.41    23.1  1873.8    34.4 1872.66
      47 1871.07    51.2 1870.32    54.9 1869.42    59.2 1867.56    63.2 1865.29
    68.1 1862.26    75.2 1858.46    79.2 1858.24    95.2 1858.75   103.2 1858.65
   111.2 1858.93   119.2 1858.76   123.2 1858.41   131.3  1858.5  136.981857.698
   139.3 1857.24   147.3 1857.69   152.4 1859.01   163.3  1862.5   171.3 1864.34
   175.3 1865.43   195.3 1870.01   203.3 1871.55   211.4 1872.88   219.6 1874.55
#Mann= 3 ,-1,0
       0      .1       0  136.98    .045       0   147.3      .1       0
Bank Sta=136.98,147.3
XS Rating Curve= 0 ,0
Exp/Cntr(USF)=0,0
Exp/Cntr=0.3,0.1

Type RM Length L Ch R = 1 ,2325    ,175.4,174.3,167.1
XS GIS Cut Line= 2
2225508.03623112708603.4886316592225572.95550511708394.960054584
#Sta/Elev= 30
       0 1876.23      15 1874.22    23.4 1873.26    33.9 1871.76    40.1 1870.78
    48.5 1869.03    56.3 1867.14    62.7 1865.16    65.9 1864.05    72.2 1861.35
    77.8 1859.23      82 1858.29    86.2    1858    97.8 1857.63     103 1857.76
   107.2 1857.21   111.3 1856.29   113.8 1856.18   119.7 1855.95   123.9 1856.02
  125.161856.173     135 1857.49   144.9 1859.19   153.2 1862.13   161.9 1864.98
   171.3  1867.7   180.9 1869.78   207.7 1874.92   211.9 1875.93   218.4 1877.72
#Mann= 3 ,-1,0
       0      .1       0   113.8    .045       0  125.16      .1       0
Bank Sta=113.8,125.16
XS Rating Curve= 0 ,0
Exp/Cntr(USF)=0,0
Exp/Cntr=0.3,0.1

Type RM Length L Ch R = 1 ,2151    ,178,173.8,170.7
XS GIS Cut Line= 2
2225682.13792047708613.3248852952225643.77653129708398.894556039
#Sta/Elev= 30
       0  1871.3    16.4    1870    20.5 1869.55    24.5 1868.71    28.6 1867.12
    32.7 1864.96    44.8    1857    47.2 1856.43      53 1855.54      57 1855.66
   60.261856.431    65.2 1857.14    69.2  1857.3    73.3 1857.87    77.4 1858.66
    81.4 1859.92    85.5 1860.83    89.5 1860.97    97.7 1860.86   101.7 1861.12
   113.9 1863.26   126.1 1864.91   142.4 1868.25   150.5 1870.36   158.6 1871.33
   162.7 1872.07   166.8 1872.29   192.9 1876.13   207.4 1879.26   217.8  1882.7
#Mann= 3 ,-1,0
       0      .1       0    47.2    .045       0   60.26      .1       0
Bank Sta=47.2,60.26
XS Rating Curve= 0 ,0
Exp/Cntr(USF)=0,0
Exp/Cntr=0.3,0.1

Type RM Length L Ch R = 1 ,1977    ,134.4,135.4,137.1
XS GIS Cut Line= 3
2225823.77997282708626.1120150212225824.76359818708535.618481574
2225762.79520028708389.058302403
#Sta/Elev= 30
       0 1872.86     5.3 1872.61    20.9  1870.6    28.9 1870.63    40.9 1869.28
    44.9 1869.47    52.9 1870.64    64.9 1869.13    68.9 1868.95    76.9 1869.48
    97.5    1868     102 1867.09   120.3 1861.93   127.9 1859.16   132.2 1858.33
   153.6 1856.31   166.1  1855.8   184.3 1853.36   188.7 1853.48  193.08 1852.88
   197.4 1852.54   202.7 1852.88   206.1 1853.67   210.4 1855.27   214.4  1858.8
   224.1 1868.29   232.1 1877.24   236.3 1881.15   240.8 1884.23   249.6 1887.82
#Mann= 3 ,-1,0
       0      .1       0  193.08    .045       0   202.7      .1       0
Bank Sta=193.08,202.7
XS Rating Curve= 0 ,0
Exp/Cntr(USF)=0,0
Exp/Cntr=0.3,0.1

Type RM Length L Ch R = 1 ,1842    ,116,113.8,112
XS GIS Cut Line= 2
2225962.99507464708585.5481955532225899.25615108708365.117751579
#Sta/Elev= 30
       0  1870.9     8.7  1869.9    21.2 1869.03    33.7 1868.72      42 1868.05
    46.2 1868.28    54.5 1867.77    62.8 1867.62    79.5 1867.98    83.7 1867.72
      92 1867.72   112.8 1866.47   121.1  1865.3   128.5 1863.05   139.8 1860.56
   154.4 1856.22   158.6 1855.43   162.8 1854.24   171.1 1851.37   176.31850.274
   179.4 1850.01  182.641850.267   183.6 1850.36   187.8 1852.32   196.1 1857.41
   200.2 1860.58   204.4 1863.07   211.8 1867.94   221.1 1875.05   229.5 1881.91
#Mann= 3 ,-1,0
       0      .1       0   176.3    .045       0  182.64      .1       0
Bank Sta=176.3,182.64
XS Rating Curve= 0 ,0
Exp/Cntr(USF)=0,0
Exp/Cntr=0.3,0.1

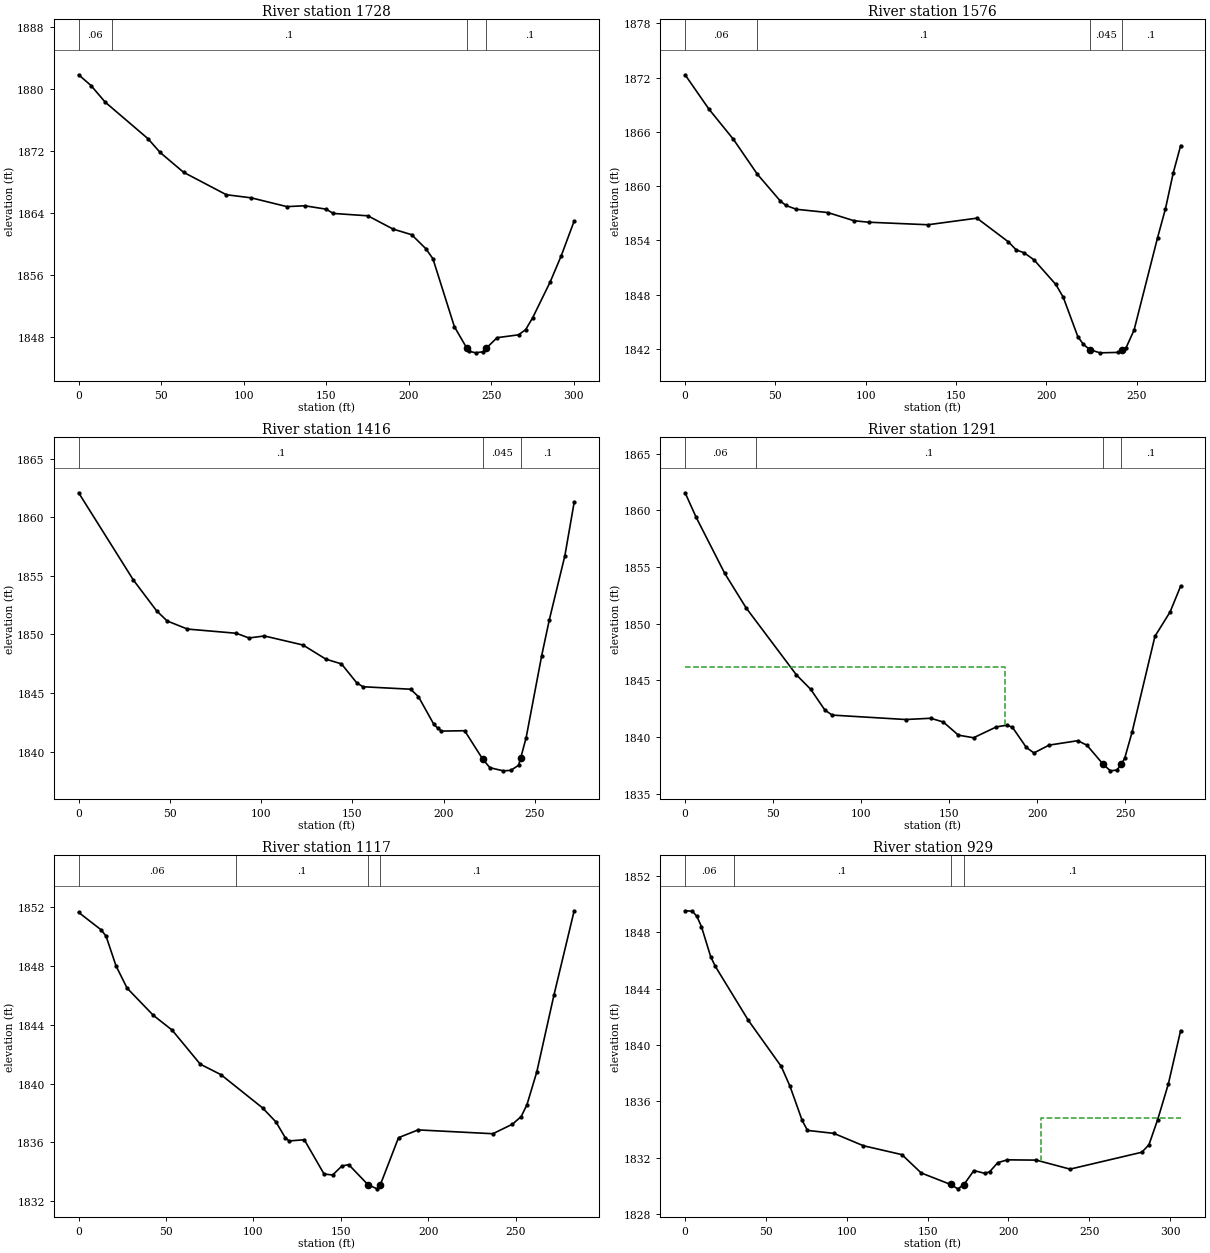
Type RM Length L Ch R = 1 ,1728    ,150.8,151.8,151.1
XS GIS Cut Line= 2
2226113.63520534708632.1064075692226000.55003266708353.942879352
#Sta/Elev= 30
       0 1881.86     7.5 1880.47    16.1 1878.32      42  1873.6    49.4 1871.81
    63.6 1869.25    89.5 1866.35   104.7 1865.94   126.2 1864.81     137 1864.92
     150 1864.48   154.3 1863.93   175.3 1863.62   190.6  1861.9   201.8 1861.18
   210.4 1859.37   214.7 1858.07   227.7 1849.29  235.271846.491   236.7 1846.11
   240.6  1845.9     245 1846.04  247.041846.507   253.6 1847.86   266.6 1848.23
   270.9  1848.9   275.2 1850.46   285.8 1855.09   292.5 1858.47   300.3 1862.95
#Mann= 4 ,-1,0
       0     .06       0      20      .1       0  235.27    .045       0
  247.04      .1       0
Bank Sta=235.27,247.04
XS Rating Curve= 0 ,0
Exp/Cntr(USF)=0,0
Exp/Cntr=0.3,0.1

Type RM Length L Ch R = 1 ,1576    ,159.1,160.6,161.9
XS GIS Cut Line= 2
2226244.85469032708557.8797698942226137.37713839 708305.44687497
#Sta/Elev= 30
       0 1872.32    13.2 1868.52    26.8 1865.17    39.9 1861.35    52.8 1858.34
    55.9 1857.86    61.6 1857.44      79 1857.08    93.6 1856.17   101.7 1856.01
   134.5 1855.73   161.6 1856.46     179 1853.84   183.4 1852.94   187.7 1852.63
   193.2 1851.85   205.3 1849.12   209.4 1847.71   217.5 1843.34   220.6 1842.49
  224.081841.919   229.7 1841.56   239.9 1841.61   241.9  1841.9   244.2 1842.13
   248.6 1844.07   261.6 1854.28     266  1857.5   270.3 1861.46   274.4 1864.48
#Mann= 4 ,-1,0
       0     .06       0      40      .1       0  224.08    .045       0
   241.9      .1       0
Bank Sta=224.08,241.9
XS Rating Curve= 0 ,0
Exp/Cntr(USF)=0,0
Exp/Cntr=0.3,0.1

Type RM Length L Ch R = 1 ,1416    ,125.1,124.5,124
XS GIS Cut Line= 2
2226369.12375262708493.6238388962226282.55510318708236.257583817
#Sta/Elev= 30
       0 1862.08      30 1854.64    42.7 1852.02    48.5 1851.15    59.6 1850.46
    86.4  1850.1    93.3  1849.7   101.8 1849.87   122.9  1849.1   135.5 1847.89
     144 1847.49   152.4 1845.87   155.8 1845.54   181.9 1845.33   186.2 1844.69
   194.6 1842.34   196.9 1841.99   198.8 1841.76   211.5 1841.79  221.331839.383
   225.3 1838.64   232.6 1838.37   236.8 1838.41     241 1838.84  242.131839.423
   245.2 1841.21   253.7 1848.19   257.9 1851.26   266.4 1856.71   271.5 1861.27
#Mann= 3 ,-1,0
       0      .1       0  221.33    .045       0  242.13      .1       0
Bank Sta=221.33,242.13
XS Rating Curve= 0 ,0
Exp/Cntr(USF)=0,0
Exp/Cntr=0.3,0.1

Type RM Length L Ch R = 1 ,1291    ,176.9,174.3,169.6
XS GIS Cut Line= 3
2226480.48156879708463.3705525962226461.93821313708359.802628043
2226398.23269496708195.549846266
#Sta/Elev= 30
       0 1861.55     6.3 1859.38    22.5 1854.44    34.7 1851.38    63.2 1845.48
    71.3 1844.21    79.4 1842.37    83.5 1841.93   125.2 1841.54   139.5 1841.65
   146.6 1841.32   155.2 1840.16   163.8 1839.93   176.8 1840.89   182.8 1841.04
   185.9 1840.85   193.8 1839.07   198.1 1838.59   206.7 1839.28     223 1839.67
   228.2 1839.27  237.321837.604   241.5 1837.01   245.3 1837.08   247.7 1837.61
   249.6  1838.1   253.9 1840.47   266.8 1848.88   275.4 1851.03   281.4 1853.31
#Mann= 4 ,-1,0
       0     .06       0      40      .1       0  237.32    .045       0
   247.7      .1       0
#XS Ineff= 2 , 0
          181.52 1846.17
Permanent Ineff=
       F       F
Bank Sta=237.32,247.7
XS Rating Curve= 0 ,0
Exp/Cntr(USF)=0,0
Exp/Cntr=0.3,0.1

Type RM Length L Ch R = 1 ,1117    ,187.5,188.3,189.1
XS GIS Cut Line= 2
2226695.82456945708295.7970730392226485.73883792708105.489809949
#Sta/Elev= 30
       0 1851.65    12.9 1850.46    15.7 1850.03    21.4 1848.01    27.7  1846.5
    42.7 1844.65    53.5 1843.64    69.6 1841.32    81.4 1840.61   105.2 1838.35
   112.9 1837.39   118.3  1836.3   120.5  1836.1   129.1 1836.18   140.4 1833.85
   145.3 1833.78   150.6 1834.39   154.5 1834.49165.49861833.127   170.7 1832.84
  172.66 1833.13     183 1836.32   194.2 1836.85     237 1836.59   248.2 1837.24
   253.2 1837.76   256.5 1838.57   262.1 1840.79     272 1846.06   283.5 1851.76
#Mann= 4 ,-1,0
       0     .06       0      90      .1       0165.4986    .045       0
  172.66      .1       0
Bank Sta=165.4986,172.66
XS Rating Curve= 0 ,0
Exp/Cntr(USF)=0,0
Exp/Cntr=0.3,0.1

Type RM Length L Ch R = 1 ,929     ,248.4,243.5,238.6
XS GIS Cut Line= 2
2226826.54003087 708185.117557112226619.96851577707958.646951106
#Sta/Elev= 30
       0 1849.53     4.5  1849.5     7.3 1849.13    10.1 1848.41    15.8 1846.28
    18.6  1845.6    39.1 1841.75    59.5 1838.47    64.9 1837.06    72.4 1834.64
    75.7 1833.93      92 1833.72   110.3 1832.84   134.1 1832.21     146 1830.91
  164.191830.092   168.7 1829.78   172.51830.085   178.6 1831.08   185.7 1830.87
   188.5 1831.01   193.4 1831.64   199.4 1831.84   217.2 1831.82   238.1 1831.18
   282.5 1832.38   286.9 1832.91   292.3  1834.7   298.9 1837.23   306.5 1841.02
#Mann= 4 ,-1,0
       0     .06       0      30      .1       0  164.19    .045       0
   172.5      .1       0
#XS Ineff= 2 , 0
                           220.1         1834.83
Permanent Ineff=
       F       F
Bank Sta=164.19,172.5
XS Rating Curve= 0 ,0
Exp/Cntr(USF)=0,0
Exp/Cntr=0.3,0.1

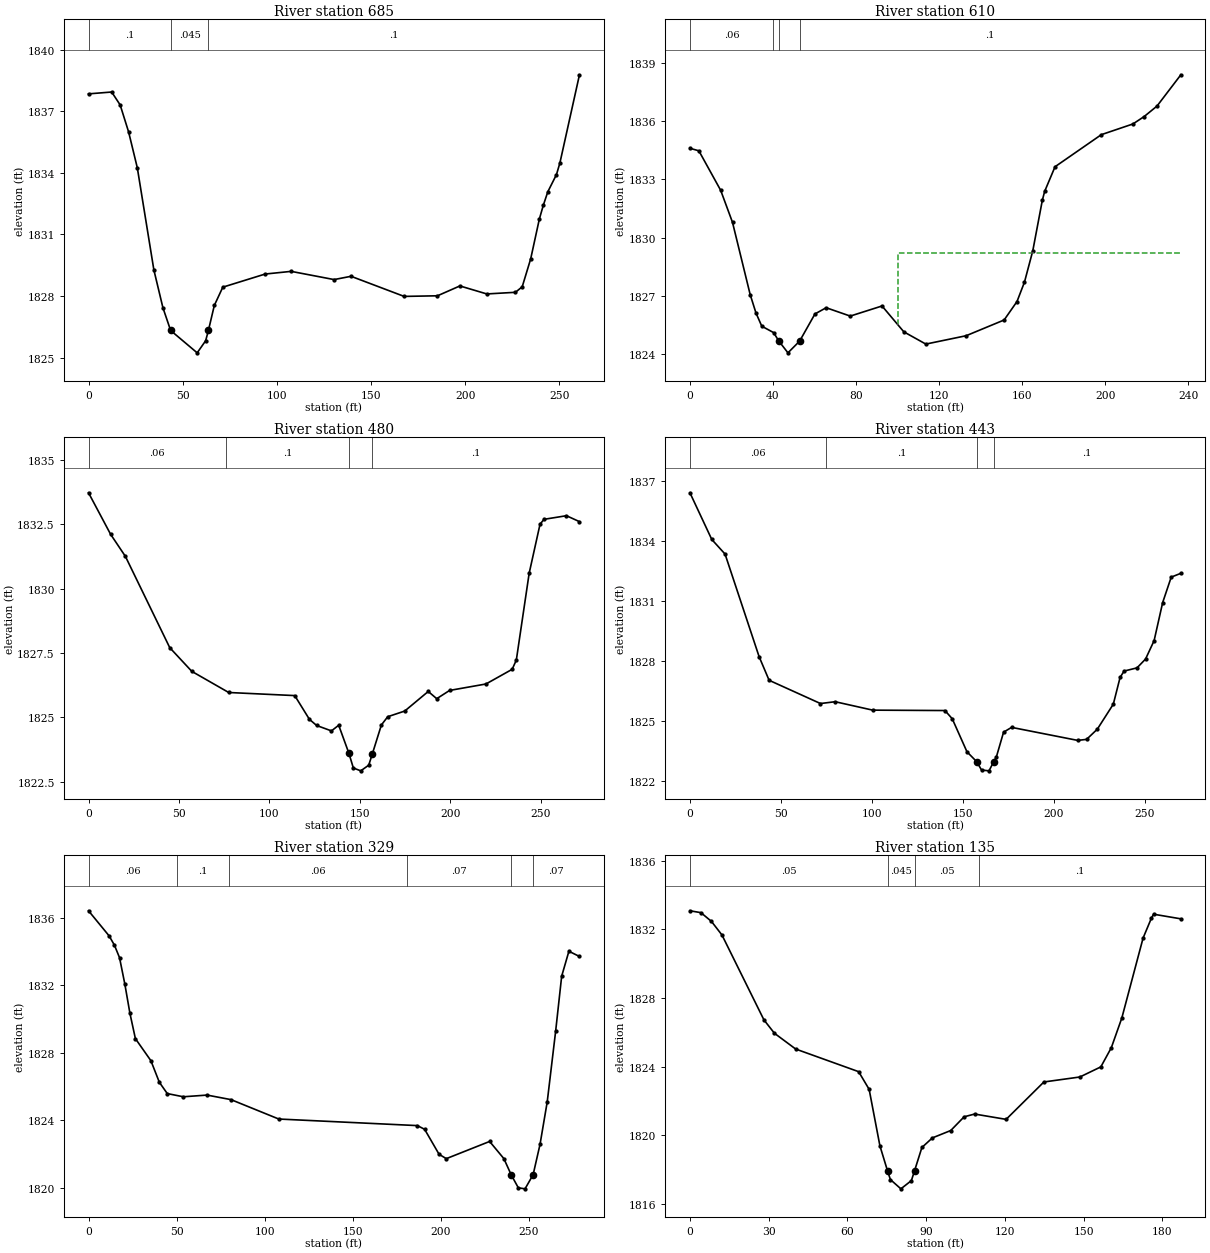
Type RM Length L Ch R = 1 ,685     ,72.8,75.2,78.8
XS GIS Cut Line= 2
2226914.97003625 707969.422538252226685.42962275707845.897524398
#Sta/Elev= 30
       0 1837.85    12.3 1837.94    16.8 1837.31    21.3 1835.99    25.9 1834.25
    34.7 1829.27    39.5 1827.43    43.6 1826.32    57.7 1825.23    62.2 1825.82
   63.671826.324    66.8 1827.54    71.3 1828.43    93.8 1829.07   107.6  1829.2
   130.4  1828.8   139.4 1828.96   167.6 1827.98   185.3 1828.01   197.2 1828.49
   211.5  1828.1   226.7 1828.18   230.3 1828.45   234.8 1829.81   239.4 1831.75
   241.5 1832.42   243.9 1833.08   248.5 1833.92   250.3 1834.48   260.7 1838.78
#Mann= 3 ,-1,0
       0      .1       0    43.6    .045       0   63.67      .1       0
Bank Sta=43.6,63.67
XS Rating Curve= 0 ,0
Exp/Cntr(USF)=0,0
Exp/Cntr=0.3,0.1

Type RM Length L Ch R = 1 ,610     ,111,130,131.8
XS GIS Cut Line= 2
2226926.97942163 707911.228648422226772.61933076707732.136830283
#Sta/Elev= 30
       0  1834.6     4.3 1834.47    14.8 1832.44    20.5 1830.79      29 1827.08
    31.8 1826.13    34.6 1825.45    40.3 1825.12    42.81824.688    47.2 1824.08
   52.841824.685    60.2 1826.08    65.6  1826.4    77.2 1825.97    92.5 1826.49
     103 1825.16   113.6 1824.53     133 1824.96   151.3 1825.77   157.5 1826.72
   161.1 1827.72   165.1 1829.33   169.7 1831.93   170.8 1832.38   175.8 1833.65
   198.1  1835.3   213.3 1835.85   218.7 1836.23   224.9 1836.77   236.4 1838.38
#Mann= 4 ,-1,0
       0     .06       0      40      .1       0    42.8    .045       0
   52.84      .1       0
#XS Ineff= 2 , 0
                          100.39         1829.19
Permanent Ineff=
       F       F
Bank Sta=42.8,52.84
XS Rating Curve= 0 ,0
Exp/Cntr(USF)=0,0
Exp/Cntr=0.3,0.1

Type RM Length L Ch R = 1 ,480     ,46.2,36.6,35.8
XS GIS Cut Line= 5
2226930.12853805707905.1614440312226945.23595629 707830.74342084
2226928.44993602707727.2296291842226956.42663647707679.669238423
2226937.96201417 707649.45440194
#Sta/Elev= 30
       0 1833.72    12.2 1832.11    20.4 1831.25    44.9 1827.71    57.1 1826.79
    77.5 1825.97     114 1825.85   122.1 1824.93   126.1 1824.69   134.3 1824.48
   138.3  1824.7  143.961823.607   146.4 1823.04   150.5 1822.93   154.9 1823.15
  156.941823.597   161.9 1824.71   165.4 1825.03   174.8 1825.25   187.8 1826.01
   192.5 1825.73   199.6 1826.05   219.7  1826.3   234.2 1826.87   236.5 1827.23
   243.6  1830.6   249.6  1832.5   251.8 1832.69   264.2 1832.83   271.4  1832.6
#Mann= 4 ,-1,0
       0     .06       0   75.94      .1       0  143.96    .045       0
  156.94      .1       0
Bank Sta=143.96,156.94
XS Rating Curve= 0 ,0
Exp/Cntr(USF)=0,0
Exp/Cntr=0.3,0.1

Type RM Length L Ch R = 1 ,443     ,114.7,114.5,115.1
XS GIS Cut Line= 5
2226965.93871462707904.3221430172226975.45079277707829.904119827
2226964.26011259707726.3903281712226992.23681304 707678.82993741
2226973.77219074707648.615100926
#Sta/Elev= 30
       0  1836.4      12 1834.07    19.3 1833.34      38 1828.22    43.5 1827.04
    71.7 1825.88    79.8 1825.97   100.4 1825.55   140.1 1825.53   144.1 1825.12
   152.2 1823.47  157.521822.979   160.2 1822.56   164.3 1822.52   166.9 1822.98
   168.3  1823.2   172.3 1824.45   176.7 1824.69     213 1824.04   217.9 1824.09
   223.8  1824.6   232.6 1825.85   236.3 1827.18   238.5  1827.5   245.6 1827.66
   250.3  1828.1     255 1829.02   259.7 1830.92   264.4 1832.19   269.7 1832.38
#Mann= 4 ,-1,0
       0     .06       0   75.02      .1       0  157.52    .045       0
   166.9      .1       0
Bank Sta=157.52,166.9
XS Rating Curve= 0 ,0
Exp/Cntr(USF)=0,0
Exp/Cntr=0.3,0.1

Type RM Length L Ch R = 1 ,329     ,194.2,194.1,194.2
XS GIS Cut Line= 3
2226983.91080357707896.7113086692227058.98427876707754.552296168
2227033.93936627707639.272264542
#Sta/Elev= 30
       0 1836.42    11.7 1834.93    14.7 1834.38    17.6 1833.64    20.6 1832.08
    23.5 1830.34    26.6 1828.84    35.4 1827.53    40.2 1826.25    44.7 1825.58
    53.8 1825.39    67.3 1825.49    80.9 1825.22     108 1824.07   186.7 1823.68
   190.8 1823.46     199 1821.98   203.1 1821.72   227.7 1822.74   235.8 1821.72
  239.981820.755     244 1819.99   247.8 1819.93  252.391820.768   256.3 1822.56
   260.4 1825.09   265.2  1829.3   268.6 1832.54   272.7 1834.02   278.7 1833.71
#Mann= 6 ,-1,0
       0     .06       0      50      .1       0      80     .06       0
  180.76     .07       0  239.98    .045       0  252.39     .07       0
Bank Sta=239.98,252.39
XS Rating Curve= 0 ,0
Exp/Cntr(USF)=0,0
Exp/Cntr=0.3,0.1

Type RM Length L Ch R = 1 ,135     ,,,
XS GIS Cut Line= 2
2227168.84923288707841.3262122192227154.55003043707654.814875902
#Sta/Elev= 30
       0 1833.09     4.2 1832.98     8.2 1832.47    12.2 1831.68    28.2 1826.73
    32.2 1825.95    40.3 1825.03    64.3 1823.71    68.3 1822.68    72.4 1819.39
    75.3 1817.93    76.4 1817.42    80.4 1816.88    84.4 1817.36    85.61817.931
    88.4 1819.29    92.4 1819.85    99.4 1820.28   104.5 1821.08   108.5 1821.24
   120.5 1820.93   134.9 1823.11   148.6  1823.4   156.6 1823.99   160.6 1825.11
   164.6 1826.84   172.7  1831.5   175.9 1832.67   176.7 1832.89   187.1 1832.62
#Mann= 4 ,-1,0
       0     .05       0    75.3    .045       0    85.6     .05       0
     110      .1       0
Bank Sta=75.3,85.6
XS Rating Curve= 0 ,0
Exp/Cntr(USF)=0,0
Exp/Cntr=0.3,0.1
LCMann Table=0

Chan Stop Cuts=-1
Use User Specified Reach Order=0
Composite Channel Slope=5